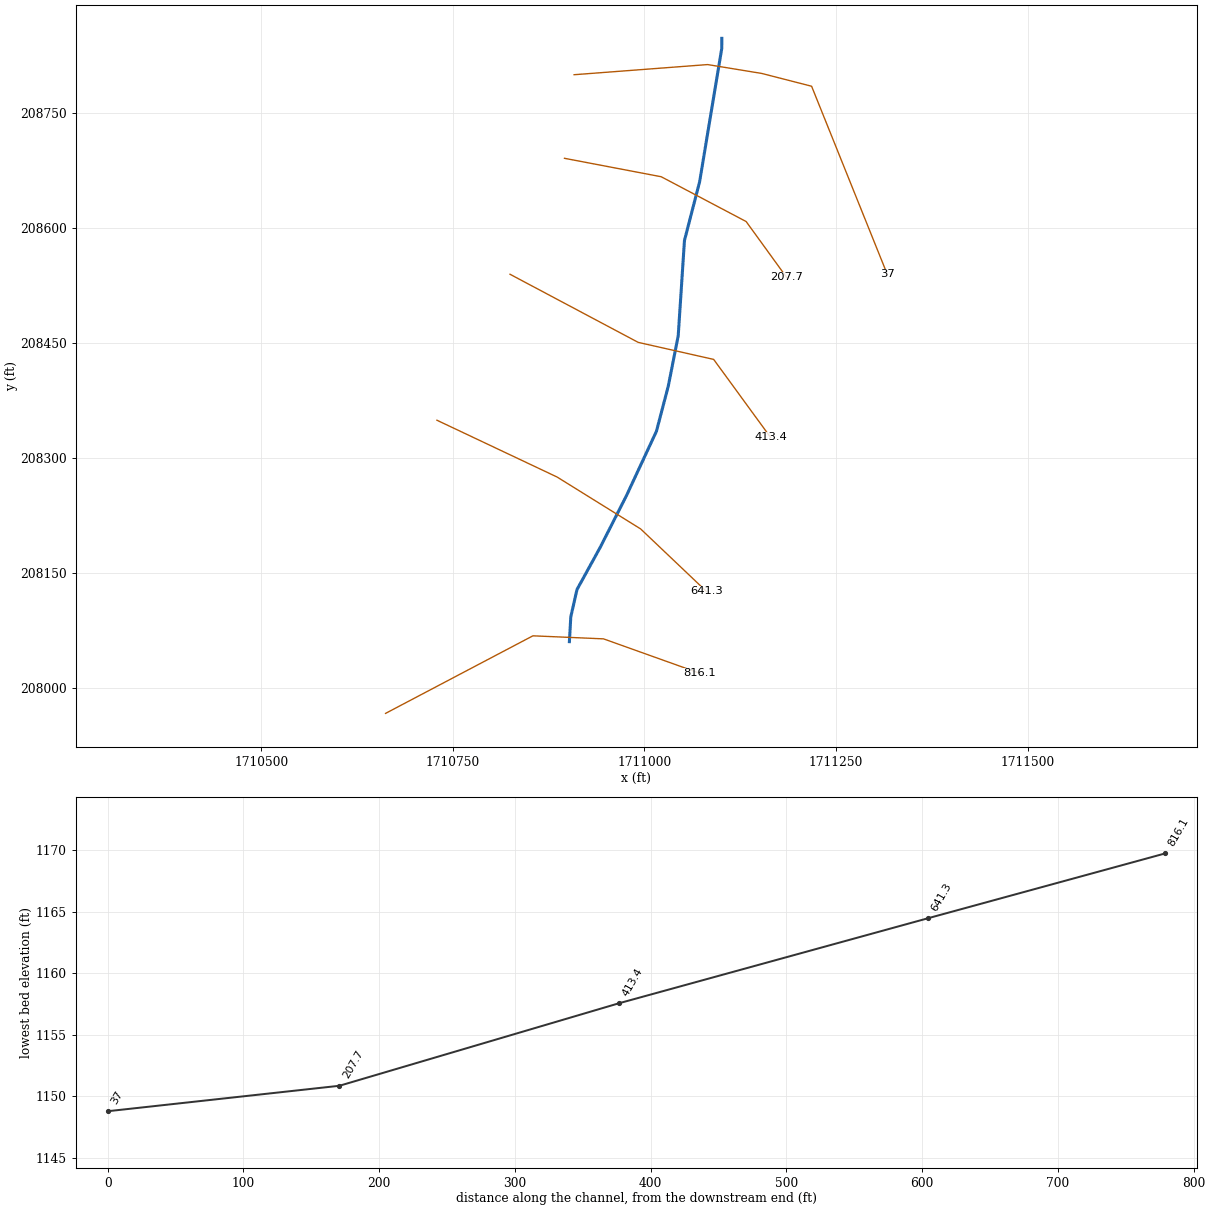
--- rghtfrkglb.prj (project) ---

Proj Title=rghtfrkglb
Current Plan=p01
Default Exp/Contr=0,0
English Units
Geom File=g01
Flow File=f01
Plan File=p01
BEGIN DESCRIPTION:
END DESCRIPTION:
DSS Export Rating Curves= 0
DSS Export Rating Curve Sorted= 0
DSS Export Volume Flow Curves= 0
DXF OffsetX= 0
DXF OffsetY= 0
DXF ScaleX= 0
DXF ScaleY= 0

--- rghtfrkglb.p01 (plan) ---

Plan Title=Floodplain
Program Version=4.00
Geom File=g01
Flow File=f01
K Sum by GR=0
Std Step Tol=0.01
Critical Tol=0.01
Num of Std Step Trials=20
Max Error Tol=0.3
Flow Tol Ratio=0.001
Split Flow NTrial=30
Split Flow Tol=0.02
Split Flow Ratio=0.02
Log Output Level=0
Friction Slope Method=1
Unsteady Friction Slope Method=2
Unsteady Bridges Friction Slope Method=1
Global Log Level=0
CheckData=False
Run HTab=0
Run UNet=0
Run PostProcess=0
UNET Theta=0
UNET Theta Warmup=0
UNET ZTol=0
UNET ZSATol=0
UNET MxIter=0
UNET MaxInSteps=0
UNET DtIC=0
UNET DtMin=0
UNET MaxCRTS=0
UNET WFStab=0
UNET SFStab=0
UNET WFX=0
UNET SFX=0
UNET DSS MLevel=0
UNET DZMax Abort=0
UNET Convert EG Bridges=0
UNET Use Existing IB Tables=0
UNET Froude Limit=0
UNET Froude Power=0
Write IC File=0
Echo Input=False
Echo Output=False
Write Detailed=0

--- rghtfrkglb.f01 (steady flow) ---

Flow Title=NFF Regression Equation
Program Version=4.00
Number of Profiles=1
Profile Names=P100yr
River Rch & RM=rghtfrkglb,Main      ,816.1
     347
River Rch & RM=rghtfrkglb,Main      ,413.4
     420
River Rch & RM=rghtfrkglb,Main      ,207.7
     422
Boundary for River Rch & Prof#=rghtfrkglb,Main      ,1
Up Type=0
Dn Type=3
Dn Slope=0.025019

--- rghtfrkglb.g01 (geometry) ---

Geom Title=USGS 10m DEM
Program Version=4.00

River Reach=rghtfrkglb      ,Main
Reach XY= 13
     1710902.141      208060.053     1710903.947      208092.288
     1710912.065      208128.105     1710921.757      208145.653
     1710942.429      208183.303       1710976.7      208250.795
     1711015.746      208334.723     1711031.128      208393.422
     1711044.151      208459.409     1711052.291       208583.74
     1711072.022      208660.161      1711100.95      208834.349
        1711101.       208847.63

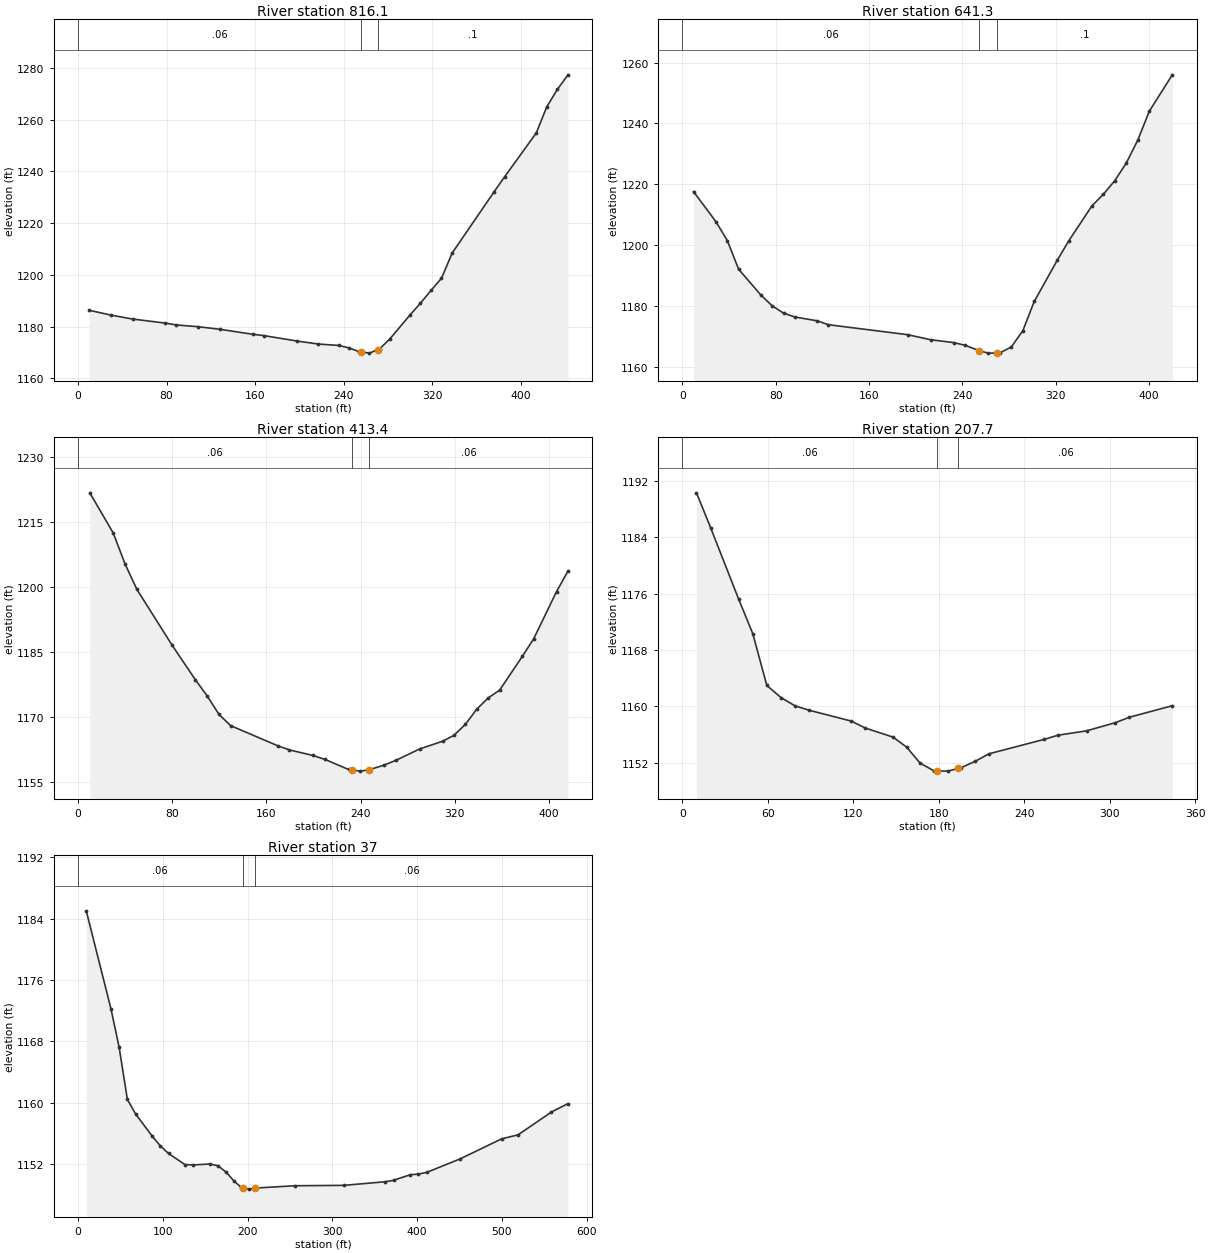
Type RM Length L Ch R = 1 ,816.1   ,186.3,174.7,163.2
XS GIS Cut Line= 4
     1710662.292      207966.396     1710854.557      208067.646
     1710946.675      208063.676     1711072.145      208018.808
#Sta/Elev= 30
     9.9 1186.32    29.6 1184.44    49.4  1182.9      79 1181.33    88.9 1180.62
   108.6 1179.94   128.4 1178.94     158 1177.01   167.9 1176.51   197.5 1174.43
   217.3 1173.24   235.7  1172.7     245 1171.73   254.2 1170.28   255.9 1170.18
   263.4 1169.73   270.9 1171.09   272.6  1171.4   281.8 1175.21   300.3  1184.6
   309.5 1189.05     319 1193.95   328.5 1198.66   338.1  1208.4   376.1 1232.14
   385.6 1237.93   414.2 1254.87   423.7 1264.99   433.2 1271.66   442.8 1277.32
#Mann= 3 , 0 , 0
       0     .06       0   255.9    .045       0   270.9      .1       0
Bank Sta=255.9,270.9
XS Rating Curve= 0 ,0
Exp/Cntr=0.3,0.1

Type RM Length L Ch R = 1 ,641.3   ,220.4,227.9,235.5
XS GIS Cut Line= 4
     1710729.351      208349.073     1710886.057      208274.955
     1710995.116       208207.19     1711080.881      208125.661
#Sta/Elev= 30
     9.6 1217.58    28.9 1207.63    38.5  1201.5    48.2 1192.08    67.4 1183.53
      77 1180.03    86.7 1177.62    96.3 1176.36   115.6 1175.09   125.2 1173.81
   193.1 1170.53   212.9 1168.87   232.6 1167.93   242.5 1167.03   254.7 1165.24
   262.2 1164.46   269.7 1164.49   272.1  1164.5     282 1166.48   291.9 1171.81
   301.7 1181.45   321.5 1195.05   331.3 1201.38   351.1 1212.87   360.9 1216.68
   370.8 1221.22   380.6 1226.96   390.5 1234.53   400.4 1244.06   420.1 1256.01
#Mann= 3 , 0 , 0
       0     .06       0   254.7    .045       0   269.7      .1       0
Bank Sta=254.7,269.7
XS Rating Curve= 0 ,0
Exp/Cntr=0.3,0.1

Type RM Length L Ch R = 1 ,413.4   ,211.7,205.7,199.6
XS GIS Cut Line= 4
     1710824.645      208539.661     1710991.939       208450.72
      1711090.41      208428.484     1711164.528      208326.837
#Sta/Elev= 30
      10 1221.75    29.9 1212.48    39.9 1205.37    49.9 1199.52    79.8 1186.64
    99.7 1178.61   109.7  1174.9   119.7 1170.64   129.6 1168.04   169.5 1163.41
   179.5 1162.44   199.6 1161.15   209.7 1160.25   229.8 1157.92   232.4 1157.82
   239.9 1157.54   247.4 1157.86   260.1 1158.94   270.2 1160.05   290.4 1162.68
   309.8 1164.44   319.4 1165.81   329.1 1168.34   338.8 1171.87   348.5 1174.43
   358.2 1176.24   377.5 1184.04   387.2 1188.14   406.5 1198.96   416.2 1203.69
#Mann= 3 , 0 , 0
       0     .06       0   232.4    .045       0   247.4     .06       0
Bank Sta=232.4,247.4
XS Rating Curve= 0 ,0
Exp/Cntr=0.3,0.1

Type RM Length L Ch R = 1 ,207.7   ,161.5,170.7,178.1
XS GIS Cut Line= 4
     1710895.754      208691.016     1711021.965       208666.95
     1711132.763      208608.484     1711185.704      208535.426
#Sta/Elev= 26
     9.9 1190.28    19.8 1185.35    39.5 1175.22    49.4 1170.33    59.3 1162.98
    69.2 1161.27    79.1 1160.09      89 1159.47   118.6 1157.93   128.5 1156.94
   147.8 1155.67   157.4 1154.25     167 1151.96   176.7 1150.88   178.8 1150.87
   186.3 1150.84   193.8 1151.23   195.9 1151.34   205.6 1152.23   215.2 1153.29
   253.8 1155.33   263.8 1155.93   283.8 1156.55   303.9  1157.7   313.9 1158.48
     344 1160.11
#Mann= 3 , 0 , 0
       0     .06       0   178.8    .045       0   193.8     .06       0
Bank Sta=178.8,193.8
XS Rating Curve= 0 ,0
Exp/Cntr=0.3,0.1

Type RM Length L Ch R = 1 ,37      ,35.3,37,40.5
XS GIS Cut Line= 5
     1710908.292      208800.131     1711082.519      208813.378
     1711153.175      208801.795      1711218.19      208785.096
     1711316.946      208539.537
#Sta/Elev= 30
     9.7    1185    38.8 1172.26    48.5 1167.24    58.2 1160.45      68 1158.54
    87.4 1155.69    97.1  1154.4   106.8 1153.41   126.2 1151.96   135.9 1151.92
   155.3 1152.04     165 1151.82   174.7 1150.99   183.7 1149.86   192.6    1149
   194.1 1148.96   201.6 1148.77   209.1 1148.91   255.9 1149.21   313.5 1149.26
   362.5 1149.73   372.3 1149.92   391.9 1150.64   401.7 1150.73   411.5 1150.95
   450.7  1152.7   499.7 1155.31   519.3 1155.84   558.5  1158.8   578.1  1159.9
#Mann= 3 , 0 , 0
       0     .06       0   194.1    .045       0   209.1     .06       0
Bank Sta=194.1,209.1
XS Rating Curve= 0 ,0
Exp/Cntr=0.3,0.1

Chan Stop Cuts=-1
Use User Specified Reach Order=0